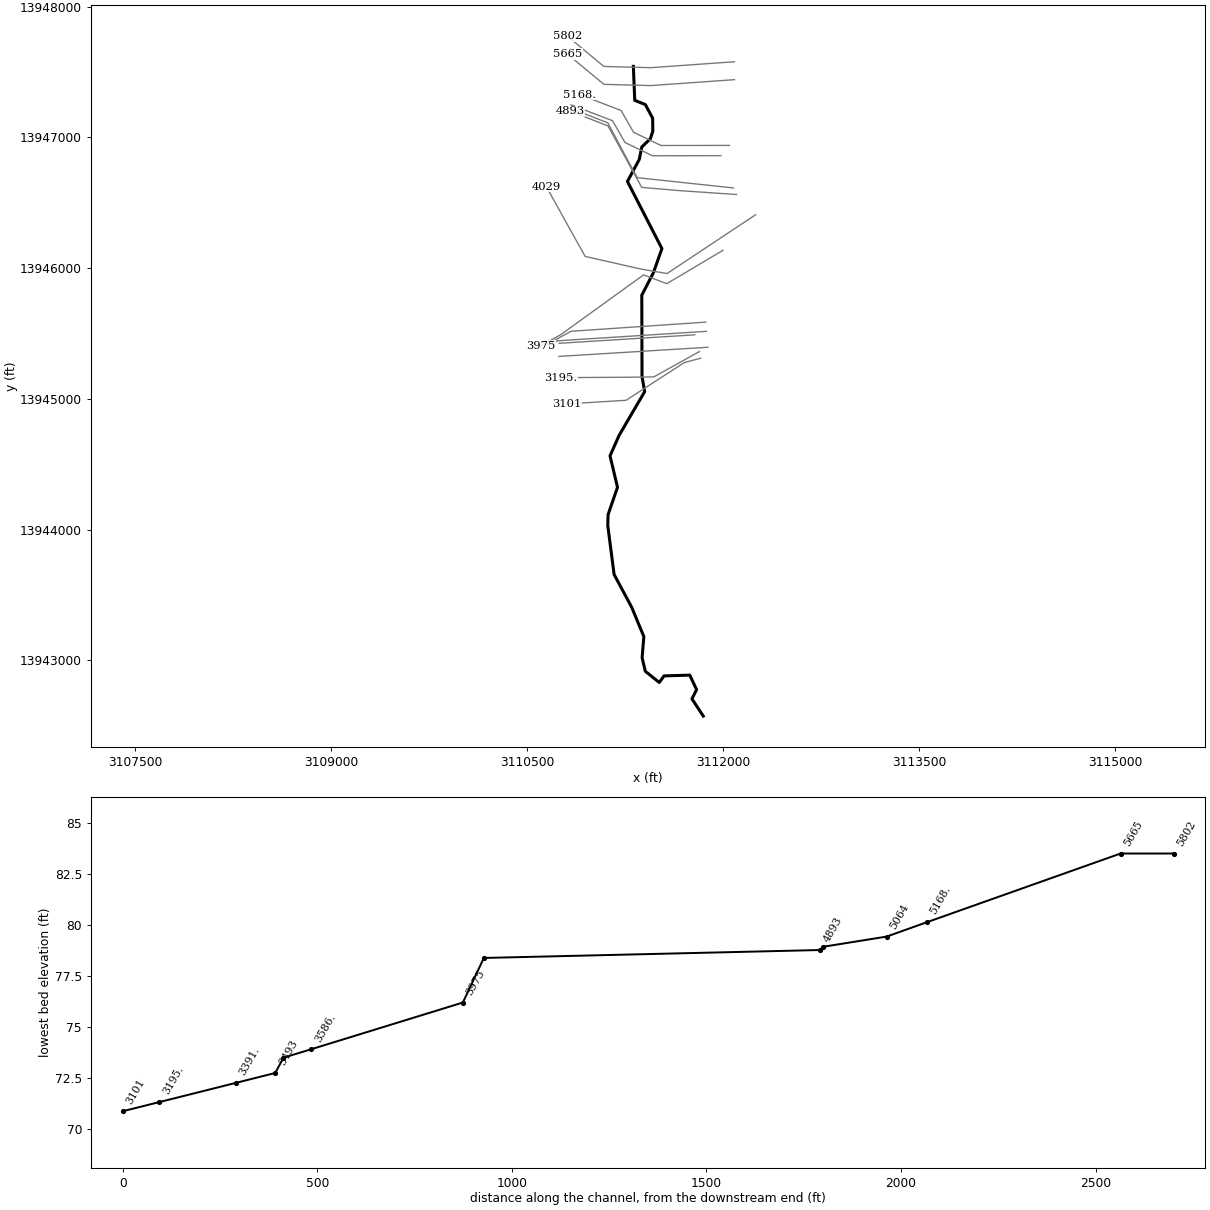
--- K116-00-00.prj (project) ---

Proj Title=K116-00-00
Current Plan=p02
Default Exp/Contr=.3,.1
English Units
Geom File=g01
Flow File=f02
Flow File=f01
Flow File=f04
Plan File=p02
Plan File=p01
Plan File=p04
Y Axis Title=Elevation
X Axis Title(PF)=Main Channel Distance
X Axis Title(XS)=Station
BEGIN DESCRIPTION:
Cypress Bayou Watershed
Schultz Gully
HCFCD Unit K116-00-00
Flood Hazard Model
10, 2, 1, 0.2%
Filename K116-00-00
Prepared by:  Halff Associates Inc  DATE:  March 26, 2004
Reviewed by:  _____________________  DATE:  __________________
STATUS (Final)
END DESCRIPTION:
DSS File=dss
DSS Export Rating Curves= 0
DSS Export Rating Curve Sorted= 0
DSS Export Volume Flow Curves= 0
DXF Filename=C:\avo\20038\Cypress\_Modeling\K116-00-00\RAS\PFPlot.dxf
DXF OffsetX= 0
DXF OffsetY= 0
DXF ScaleX= 1
DXF ScaleY= 10

--- K116-00-00.p02 (plan) ---

Plan Title=Floodway
Version=Version 3.0.1  Mar 2001
Short Identifier=Floodway0607
Geom File=g01
Flow File=f02
Subcritical Flow
K Sum by GR= 0
Std Step Tol= 0.01
Critical Tol= 0.01
Num of Std Step Trials= 20
Max Error Tol= 0.3
Flow Tol Ratio= 0.001
Split Flow NTrial= 30
Split Flow Tol= 0.02
Split Flow Ratio= 0.02
Log Output Level= 0
Friction Slope Method= 1
Unsteady Friction Slope Method= 2
Parabolic Critical Depth
Global Vel Dist= 0 , 0 , 0
Global Log Level= 0
CheckData=True
Encroach Param=-1 ,0,0, 2
Encroach River=K116-00-00
Encroach Reach=Reach - 1
Encroach Node=5802
       1 4855.38  5022.8
Encroach Node=5665
       1 4851.02  5022.8
Encroach Node=5168.
       1  4939.1  5119.9
Encroach Node=5064
       1  4939.1  5119.9
Encroach Node=4982.5
       1  4939.1  5119.9
Encroach Node=4901
       1  4952.9 5185.94
Encroach Node=4893
       1  4952.9 5185.94
Encroach Node=4461
       1  4952.9 5185.94
Encroach Node=4029
       1 4966.78 5017.85
Encroach Node=3975
       1  4938.8  5058.8
Encroach Node=3586.
       1  4955.1  5045.1
Encroach Node=3514
       1  4962.6  5052.9
Encroach Node=3503.5
       1  4962.6  5052.9
Encroach Node=3493
       1  4962.6  5052.9
Encroach Node=3391.
       1  4940.2  5050.2
Encroach Node=3195.
       1  4929.9  5039.9
Encroach Node=3101
       1 3802.52  3886.1
Encroach Node=3090.5
       1 3802.52  3886.1
Encroach Node=3080
       1 3802.52  3886.1
Encroach Node=2863.
       1  4948.2  5048.2
Encroach Node=1861.
       1  4940.3  5050.3
Encroach Node=1768
       1    4964  5039.3
Encroach Node=1757.5
       1    4964  5039.3
Encroach Node=1747
       1  4971.2  5028.7
Encroach Node=1523
       1  4918.5  5058.5
Encroach Reach=K116-00-00_0015
Encroach Node=5802
       1 4855.38  5022.8
Encroach Node=5665
       1 4851.02  5022.8
Encroach Node=5168.
       1  4939.1  5119.9
Encroach Node=5064
       1  4939.1  5119.9
Encroach Node=4982.5
       1  4939.1  5119.9
Encroach Node=4901
       1  4952.9 5185.94
Encroach Node=4893
       1  4952.9 5185.94
Encroach Node=4461
       1  4952.9 5185.94
Encroach Node=4029
       1 4966.78 5017.85
Encroach Node=3975
       1  4938.8  5058.8
Encroach Node=3586.
       1  4955.1  5045.1
Encroach Node=3514
       1  4962.6  5052.9
Encroach Node=3503.5
       1  4962.6  5052.9
Encroach Node=3493
       1  4962.6  5052.9
Encroach Node=3391.
       1  4940.2  5050.2
Encroach Node=3195.
       1  4929.9  5039.9
Encroach Node=3101
       1 3802.52  3886.1
Encroach Node=3090.5
       1 3802.52  3886.1
Encroach Node=3080
       1 3802.52  3886.1
Encroach Node=2863.
       1  4948.2  5048.2
Encroach Node=1861.
       1  4940.3  5050.3
Encroach Node=1768
       1    4964  5039.3
Encroach Node=1757.5
       1    4964  5039.3
Encroach Node=1747
       1  4971.2  5028.7
Encroach Node=1523
       1  4918.5  5058.5
Computation Interval=1HOUR
Output Interval=1HOUR
Run HTab= 0
Run UNet= 0
Run PostProcess= 0
UNET Theta= 1
UNET ZTol= 0.02
UNET ZSATol= 0.1
UNET MxIter= 20
UNET MaxInSteps= 20
UNET DtIC= 0
UNET DtMin= 0
UNET MaxCRTS= 20
UNET WFStab= 2
UNET SFStab= 1
UNET WFX= 1
UNET SFX= 1
UNET Convert EG Bridges=-1
UNET Use Existing IB Tables=-1
Instantaneous Interval=1HOUR
Write IC File= 0
Write Velocity= 0
Write Detailed= 0

--- K116-00-00.p01 (plan) ---

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Plan Title=FEMA Effective June 2007
Short Identifier=FEMAeff0607
Geom File=g01
Flow File=f01
Encroach Param=-1 ,0,0, 0
DSS File=dss
IC Time=0

--- K116-00-00.p04 (plan) ---

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Plan Title=Storage Routing
Short Identifier=Store_Rout
Geom File=g01
Flow File=f04
Encroach Param=-1 ,0,0, 0

--- K116-00-00.f02 (steady flow) ---

Flow Title=Floodway
Version=Version 3.0.1  Mar 2001
Number of Profiles= 2
Profile Names=1PCT_100yr, 1PCTFloodway_100yrFW
River Rch & RM=K116-00-00,K116-00-00_0015,5802
    2050    2050
River Rch & RM=K116-00-00,K116-00-00_0015,4893
    2140    2140
River Rch & RM=K116-00-00,K116-00-00_0015,4029
    2290    2290
River Rch & RM=K116-00-00,K116-00-00_0015,3514
    2340    2340
River Rch & RM=K116-00-00,K116-00-00_0015,3101
    2470    2470
River Rch & RM=K116-00-00,K116-00-00_0015,1747
    2652    2652
Boundary for River Rch & Prof#=K116-00-00,K116-00-00_0015, 1
Up Type= 0
Dn Type= 3
Dn Slope=.002
Boundary for River Rch & Prof#=K116-00-00,K116-00-00_0015, 2
Up Type= 0
Dn Type= 3
Dn Slope=.002
DSS Import GetInterval= 0
DSS Import GetPeak= 0
DSS Import FillOption= 0

--- K116-00-00.f01 (steady flow) ---

Flow Title=FEMA Effective June 2007
Version=Version 3.0.1  Mar 2001
Number of Profiles= 4
Profile Names=10PCT_10yr, 2PCT_50yr, 1PCT_100yr, 0.2PCT_500yr
River Rch & RM=K116-00-00,K116-00-00_0015,5802
    1280    1830    2050    2770
River Rch & RM=K116-00-00,K116-00-00_0015,4893
    1340    1910    2140    2870
River Rch & RM=K116-00-00,K116-00-00_0015,4029
    1420    2030    2290    3070
River Rch & RM=K116-00-00,K116-00-00_0015,3514
    1440    2070    2340    3140
River Rch & RM=K116-00-00,K116-00-00_0015,3101
    1500    2170    2470    3350
River Rch & RM=K116-00-00,K116-00-00_0015,1747
  1580.1    2319    2652    3657
Boundary for River Rch & Prof#=K116-00-00,K116-00-00_0015, 1
Up Type= 0
Dn Type= 3
Dn Slope=.002
Boundary for River Rch & Prof#=K116-00-00,K116-00-00_0015, 2
Up Type= 0
Dn Type= 3
Dn Slope=.002
Boundary for River Rch & Prof#=K116-00-00,K116-00-00_0015, 3
Up Type= 0
Dn Type= 3
Dn Slope=.002
Boundary for River Rch & Prof#=K116-00-00,K116-00-00_0015, 4
Up Type= 0
Dn Type= 3
Dn Slope=.002
DSS Import GetInterval= 0
DSS Import GetPeak= 0
DSS Import FillOption= 0

--- K116-00-00.f04 (steady flow) ---

Flow Title=Storage Routing
Version=Version 3.0.1  Mar 2001
Number of Profiles= 8
Profile Names=0.25*10% flood, 0.50*10%flood, 10% flood, 4% flood, 2% flood, 1% flood, 0.2%flood, 1.25*0.2% flood
River Rch & RM=K116-00-00,K116-00-00_0015,5802
      18      35      70     120     160     220     260     330
River Rch & RM=K116-00-00,K116-00-00_0015,5064
      45      90     180     250     310     390     470     590
River Rch & RM=K116-00-00,K116-00-00_0015,4893
      70     140     280     370     460     560     680     850
River Rch & RM=K116-00-00,K116-00-00_0015,3975
     118     235     470     580     680     800     980    1230
River Rch & RM=K116-00-00,K116-00-00_0015,3101
     163     325     650     780     900    1030    1270    1590
Boundary for River Rch & Prof#=K116-00-00,K116-00-00_0015, 1
Up Type= 0
Dn Type= 3
Dn Slope=.002
Boundary for River Rch & Prof#=K116-00-00,K116-00-00_0015, 2
Up Type= 0
Dn Type= 3
Dn Slope=.002
Boundary for River Rch & Prof#=K116-00-00,K116-00-00_0015, 3
Up Type= 0
Dn Type= 3
Dn Slope=.002
Boundary for River Rch & Prof#=K116-00-00,K116-00-00_0015, 4
Up Type= 0
Dn Type= 3
Dn Slope=.002
Boundary for River Rch & Prof#=K116-00-00,K116-00-00_0015, 5
Up Type= 0
Dn Type= 3
Dn Slope=.002
Boundary for River Rch & Prof#=K116-00-00,K116-00-00_0015, 6
Up Type= 0
Dn Type= 3
Dn Slope=.002
Boundary for River Rch & Prof#=K116-00-00,K116-00-00_0015, 7
Up Type= 0
Dn Type= 3
Dn Slope=.002
Boundary for River Rch & Prof#=K116-00-00,K116-00-00_0015, 8
Up Type= 0
Dn Type= 3
Dn Slope=.002
DSS Import GetInterval= 0
DSS Import GetPeak= 0
DSS Import FillOption= 0

--- K116-00-00.g01 (geometry) ---

Geom Title=K116-00-00 June 2007
Version=Version 3.0.1  Mar 2001

River Reach=K116-00-00      ,K116-00-00_0015
Reach XY= 30
      3111312.37      13947544.4      3111322.95     13947284.34
      3111404.33     13947251.79      3111459.94     13947147.35
       3111461.3     13947048.34      3111442.24      13946990.7
      3111376.87     13946927.01      3111357.31     13946831.29
      3111267.03     13946663.76       3111530.9     13946149.83
      3111465.12     13945963.71      3111376.86     13945793.37
      3111378.59     13945170.11      3111398.92     13945055.45
      3111203.24     13944720.46       3111133.8     13944564.21
      3111191.09     13944323.75      3111119.04     13944114.55
      3111116.44     13944032.09      3111165.05     13943656.22
      3111300.47     13943403.62      3111392.48     13943181.39
      3111379.46     13943019.07      3111403.76     13942915.77
      3111510.54     13942829.83      3111546.99     13942880.18
      3111744.04     13942886.25      3111796.13     13942775.14
      3111760.54     13942704.83      3111847.34      13942572.8

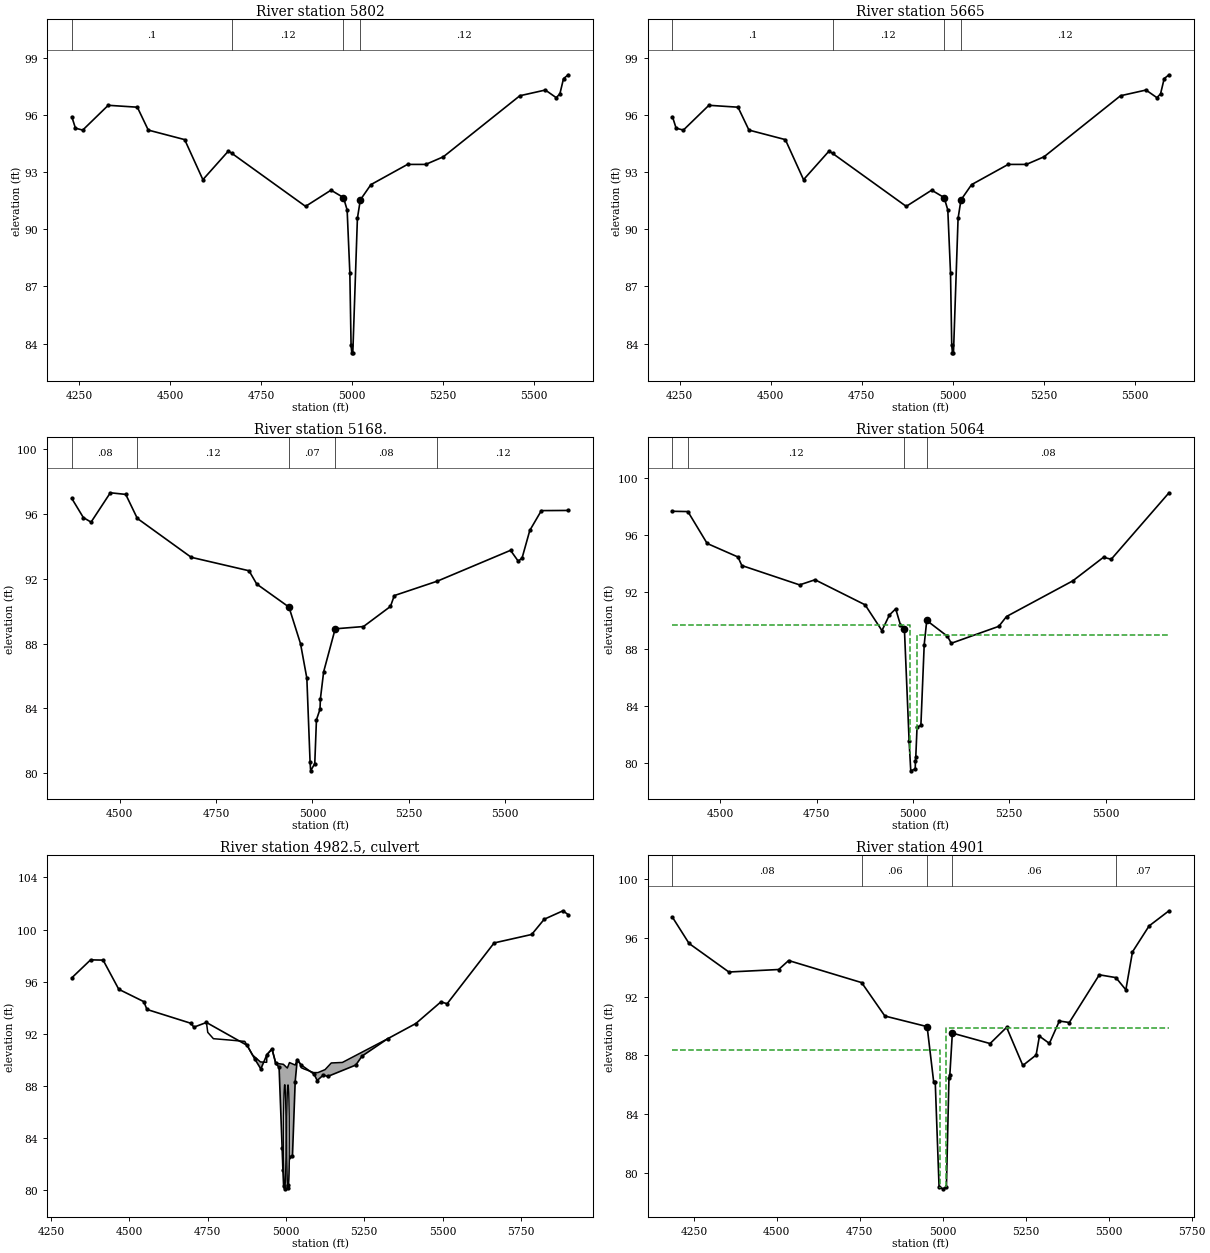
Type RM Length L Ch R = 1 ,5802    ,136,137,138
BEGIN DESCRIPTION:
Cross Section K116-00-00-X02
END DESCRIPTION:
XS GIS Cut Line= 4
      3112085.76      13947579.5      3111445.38      13947534.1
      3111086.95      13947543.6      3110807.38      13947775.4
#Sta/Elev= 30
  4230.4    95.9  4240.4    95.3  4260.4    95.2  4330.4    96.5  4410.4    96.4
  4440.4    95.2  4540.4    94.7  4590.4    92.6  4660.4    94.1    4670   93.98
  4872.4    91.2  4942.3   92.05  4976.6   91.66  4986.6   91.01    4994   87.73
  4997.4   83.93  4999.3   83.52  5002.2   83.53  5014.8   90.57  5022.8   91.54
  5051.9   92.34  5152.4    93.4  5202.4    93.4  5250.9    93.8  5460.9      97
  5530.9    97.3  5560.9    96.9  5570.9    97.1  5580.9    97.9  5594.1    98.1
#Mann= 4 ,-1 , 0
  4230.4      .1       0    4670     .12       0  4976.6     .06       0
  5022.8     .12       0
Bank Sta=4976.6,5022.8
XS Rating Curve= 0
Exp/Cntr=.3,.1

Type RM Length L Ch R = 1 ,5665    ,508.7,497,357
BEGIN DESCRIPTION:
Cross Section K116-00-00-X02
END DESCRIPTION:
XS GIS Cut Line= 4
      3112085.76     13947442.52      3111445.38     13947397.12
      3111086.95     13947406.68      3110807.38     13947638.46
#Sta/Elev= 30
  4230.4    95.9  4240.4    95.3  4260.4    95.2  4330.4    96.5  4410.4    96.4
  4440.4    95.2  4540.4    94.7  4590.4    92.6  4660.4    94.1    4670   93.98
  4872.4    91.2  4942.3   92.05  4976.6   91.66  4986.6   91.01    4994   87.73
  4997.4   83.93  4999.3   83.52  5002.2   83.53  5014.8   90.57  5022.8   91.54
  5051.9   92.34  5152.4    93.4  5202.4    93.4  5250.9    93.8  5460.9      97
  5530.9    97.3  5560.9    96.9  5570.9    97.1  5580.9    97.9  5594.1    98.1
#Mann= 4 ,-1 , 0
  4230.4      .1       0    4670     .12       0  4976.6     .06       0
  5022.8     .12       0
Bank Sta=4976.6,5022.8
XS Rating Curve= 0
Exp/Cntr=.3,.1

Type RM Length L Ch R = 1 ,5168.   ,106.3,104,102
BEGIN DESCRIPTION:
DBL CULV 30' U/S ALDINE WESTFIELD - XS 4
Interpolated channel - LIDAR overbanks.
END DESCRIPTION:
XS GIS Cut Line= 5
      3112047.49     13946939.42      3111523.77     13946938.71
      3111313.54     13947040.12      3111218.71     13947206.64
       3110901.1     13947328.18
#Sta/Elev= 30
  4375.4   96.95  4405.4   95.77  4425.4   95.49  4475.4    97.3  4515.4    97.2
  4545.4   95.72  4685.4   93.32  4835.4   92.49  4855.4   91.67  4939.1   90.25
  4969.1   87.99  4985.5   85.86 4993.86    80.7 4995.33   80.15 5006.06    80.6
 5010.41    83.3 5019.66   83.95 5020.65   84.59  5029.1   86.26  5059.1   88.91
  5132.5   89.05  5202.5   90.29  5212.5   90.96  5324.2   91.85  5514.2   93.75
  5534.2   93.08  5544.2   93.28  5564.2   94.98  5594.2    96.2  5664.2   96.21
#Mann= 5 ,-1 , 0
  4375.4     .08       0  4545.4     .12       0  4939.1     .07       0
  5059.1     .08       0  5324.2     .12       0
Bank Sta=4939.1,5059.1
XS Rating Curve= 0
Exp/Cntr=.5,.3

Type RM Length L Ch R = 1 ,5064    ,184.3,163,100.3
BEGIN DESCRIPTION:
DBL CULV 30' U/S ALDINE WESTFIELD - XS 3
Upstream Section of Bridge/Culvert/Weir
END DESCRIPTION:
XS GIS Cut Line= 5
      3111982.15       13946861.      3111458.42      13946860.3
       3111248.2      13946961.7      3111153.36      13947128.2
      3110835.75      13947249.7
#Sta/Elev= 30
    4376   97.67    4416   97.65    4466   95.41    4546   94.46    4556   93.86
    4706    92.5    4746   92.86    4876    91.1  4919.7   89.29    4939   90.38
  4955.4   90.82  4967.5   89.71    4978   89.42  4990.2   81.56  4994.5   79.44
  5006.1   79.57  5006.6   80.14  5007.5   80.38  5010.8    82.5  5020.8   82.63
  5029.4    88.3    5036      90  5089.7   88.89  5099.7    88.4  5223.1   89.59
  5243.1   90.28  5414.8   92.78  5494.8   94.44  5514.8    94.3  5664.8   98.97
#Mann= 4 ,-1 , 0
    4376     .08       0    4416     .12       0    4978     .07       0
    5036     .08       0
#XS Ineff= 2 , 0
       0 4992.08   89.69 5010.49       0   89.01
Permanent Ineff=
       F       F
Bank Sta=4978,5036
XS Rating Curve= 0
Exp/Cntr=.5,.3

Type RM Length L Ch R = 2 ,4982.5  ,,,
BEGIN DESCRIPTION:
DBL CULV 30' U/S ALDINE WESTFIELD
Structure ID: K116-00-00-S6
Pipe appears to be concrete from picture VRR
END DESCRIPTION:
Bridge Culvert--1,0,-1,-1, 0
Deck Dist Width WeirC Skew NumUp NumDn MinLoCord MaxHiCord MaxSubmerge Is_Ogee
10,143,2.6,0, 41, 38, , , .95, 0, 0,0,,
    4746  4750.2  4768.4  4770.2  4820.2  4852.1  4868.4  4893.3  4918.4  4938.3
  4938.4    4939  4955.4  4967.5    4978  4987.7  4990.2  4991.5  4992.5  4994.5
  4995.6  5000.2  5004.4  5006.1  5006.6  5007.5  5010.8  5011.2  5020.8  5029.4
    5036  5047.6  5048.4  5058.4  5058.8  5088.4  5102.1  5124.9  5144.7  5180.2
  5324.8
   92.86    92.1   91.61   91.61   91.51   91.44   91.41   90.36   89.83    89.8
    89.8   90.39   90.83   89.72   89.69   89.66   89.65   89.65   89.63   89.58
   89.56   89.45   89.36   89.47    89.5   89.55   89.76   89.78   89.68   89.59
   90.01   89.62   89.39   89.28   89.28   89.01   89.01   89.24   89.75   89.79
   91.61
                                                                                
                                                                                
                                                                                
                                                                                
        
    4746  4750.2  4768.4  4770.2  4820.2  4852.1  4868.4  4893.3  4918.4  4938.3
  4938.4  4967.5    4978  4987.7  4990.2  4991.5  4992.5  4994.5  4995.6  5000.2
  5004.4  5006.1  5006.6  5007.5  5010.8  5011.2  5020.8  5029.4  5048.4  5058.4
  5058.8  5088.4  5102.1  5124.9  5144.7  5180.2  5324.8  5471.7
   92.86    92.1   91.61   91.61   91.51   91.44   91.41   90.36   89.83    89.8
    89.8   89.72   89.69   89.66   89.65   89.65   89.63   89.58   89.56   89.45
   89.36   89.47    89.5   89.55   89.76   89.78   89.68   89.59   89.39   89.28
   89.28   89.01   89.01   89.24   89.75   89.79   91.61   93.48
                                                                                
                                                                                
                                                                                
                                                                
BR Coef= 1 , 1 , 0 ,1.25, 0 ,,,.8,0,2,0,
WSPro=,,,, 1 ,,,, 0 ,,,, 0 ,,,,-1 ,-1 ,-1 , 0 , 0 , 0 , 0 , 0
Culvert=1,8,,143,.013,.5,1,1,2,80.09,4996.1,79.62,4996.1,Culvert #1  , 0 ,10
Culvert Bottom n=.013
Culvert=1,8,,143,.013,.5,1,1,2,80.08,5006.5,79.56,5006.5,Culvert #2  , 0 ,10
Culvert Bottom n=.013
BR U #Sta/Elev= 42
    4316   96.29    4376   97.67    4416   97.65    4466   95.41    4546   94.46
    4556   93.86    4696    92.8    4706    92.5    4746   92.86    4876    91.1
  4899.7   90.08  4919.7   89.29    4939   90.38  4955.4   90.82  4967.5   89.71
    4978   89.42  4987.7   83.23  4990.2   81.56  4992.5   80.29  4995.6   80.08
  5006.6   80.14  5007.5   80.38  5010.8    82.5  5020.8   82.63  5029.4    88.3
    5036      90  5047.6   89.61  5089.7   88.89  5099.7    88.4  5119.7   88.83
  5133.1   88.71  5223.1   89.59  5243.1   90.28  5324.8   91.61  5414.8   92.78
  5494.8   94.44  5514.8    94.3  5664.8   98.97  5784.8   99.62  5824.8  100.79
  5884.8  101.44  5901.8  101.13
BR U #Mann= 4
    4316     .08    4416     .12    4978     .07    5036     .08
BR D #Sta/Elev= 52
  4085.6   95.54  4105.6    95.9  4115.6   96.69  4185.6   97.39  4235.6   95.61
  4265.6   95.47  4345.6    94.3  4355.6   93.67  4405.6    93.7  4435.6   94.35
  4505.6   93.84  4535.6   94.45  4615.6   93.49  4755.6   92.95  4805.6   91.66
  4825.6   90.68  4899.3   90.03  4952.9   89.96  4972.5   86.85  4977.3   86.84
  4988.9   79.68  5000.9   79.56    5011   79.67  5018.7   87.09  5021.3   87.28
  5028.9   89.52    5092   89.44  5142.6   88.81  5192.4   89.91  5221.3   88.85
  5241.3   87.32  5251.3   87.97  5281.3   88.03  5291.3   89.31  5311.3   88.75
  5321.3   88.82  5341.3   89.55  5351.3   90.34  5381.3   90.24  5401.3   91.29
  5401.7   91.31  5471.7   93.48  5521.7   93.29  5541.7   92.26  5551.7   92.46
  5571.7   95.04  5621.7    96.8  5681.7   97.83  5711.7    99.1  5821.7   99.87
  5841.7  100.81  5950.1  101.48
BR D #Mann= 5
  4085.6     .08  4755.6     .06  4952.9     .03  5028.9     .06  5521.7     .07
BC Design=,, 0 ,, 0 ,,,,,,
BC HTab HWMax=98.97

Type RM Length L Ch R = 1 ,4901    ,8,8,8
BEGIN DESCRIPTION:
DBL CULV 30' U/S ALDINE WESTFIELD  - XS 2
Data replaced with data from d/s XS 4912.8
Downstream Section of Bridge/Culvert/Weir
END DESCRIPTION:
XS GIS Cut Line= 5
      3112078.12      13946613.9      3111343.18      13946692.4
      3111281.57      13946802.9      3111116.99      13947112.2
      3110856.05      13947213.8
#Sta/Elev= 30
  4185.6   97.39  4235.6   95.61  4355.6   93.67  4505.6   93.84  4535.6   94.45
  4755.6   92.95  4825.6   90.68  4952.9   89.96  4972.5   86.23  4977.3   86.22
  4988.9   79.06  5000.9   78.94    5011   79.05  5018.7   86.47  5021.3   86.66
  5028.9   89.52  5142.6   88.81  5192.4   89.91  5241.3   87.32  5281.3   88.03
  5291.3   89.31  5321.3   88.82  5351.3   90.34  5381.3   90.24  5471.7   93.48
  5521.7   93.29  5551.7   92.46  5571.7   95.04  5621.7    96.8  5681.7   97.83
#Mann= 5 ,-1 , 0
  4185.6     .08       0  4755.6     .06       0  4952.9     .03       0
  5028.9     .06       0  5521.7     .07       0
#XS Ineff= 2 , 0
       0 4992.08    88.4 5010.49       0    89.9
Permanent Ineff=
       F       F
Bank Sta=4952.9,5028.9
XS Rating Curve= 0
Exp/Cntr=.5,.3

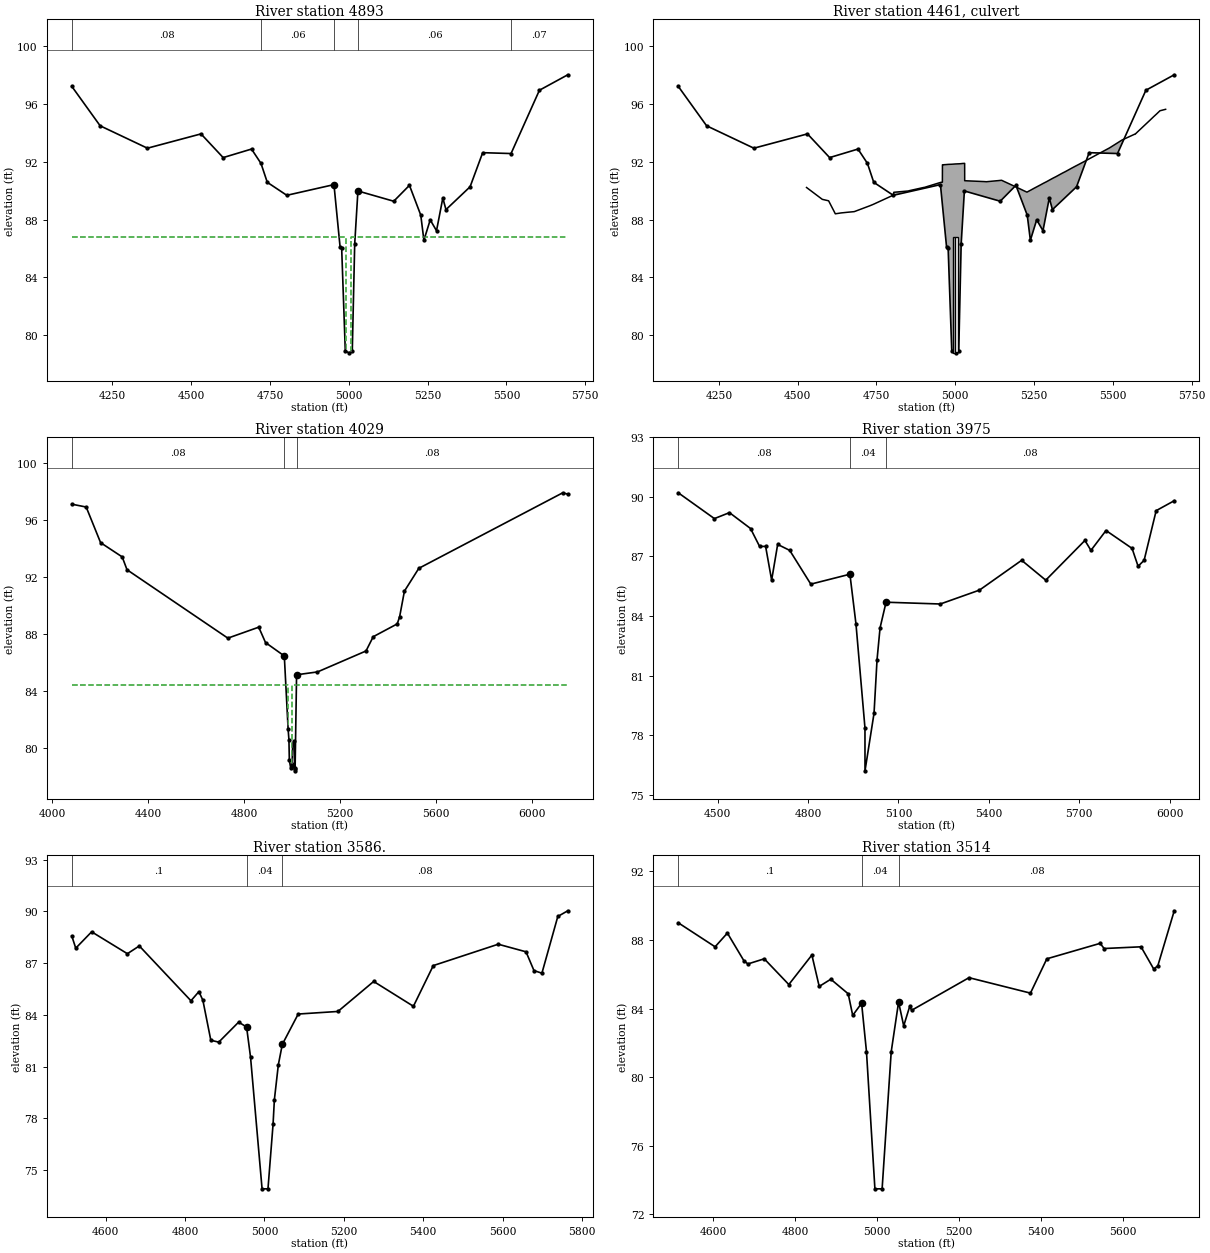
Type RM Length L Ch R = 1 ,4893    ,730.4,864,874.9
BEGIN DESCRIPTION:
Aldine Westfield Rd. US - XS 3
Upstream Section of Bridge/Culvert/Weir
END DESCRIPTION:
XS GIS Cut Line= 5
      3112101.66      13946563.8      3111672.35      13946592.8
      3111376.39      13946618.2      3111118.53      13947088.6
      3110829.78      13947201.3
#Sta/Elev= 30
    4121   97.22    4211   94.49    4361   92.94    4531   93.93  4601.3   92.29
  4691.3   92.88  4721.3   91.89  4741.3   90.58  4803.3   89.68  4952.9   90.42
  4972.5   86.07  4977.3   86.06  4988.9    78.9  5000.9   78.78    5011   78.89
  5018.7   86.31  5028.9   89.98  5142.6   89.27  5192.4   90.37  5228.3   88.31
  5238.3   86.57  5258.3   87.98  5278.3   87.23  5298.3   89.49  5308.3   88.69
  5384.8   90.27  5424.8   92.63  5514.8   92.57  5604.8   96.95  5694.8   98.02
#Mann= 5 ,-1 , 0
    4121     .08       0  4721.3     .06       0  4952.9     .03       0
  5028.9     .06       0  5514.8     .07       0
#XS Ineff= 2 , 0
       0  4991.5   86.78  5008.5       0   86.81
Permanent Ineff=
       F       F
Bank Sta=4952.9,5028.9
XS Rating Curve= 0
Exp/Cntr=.5,.3

Type RM Length L Ch R = 2 ,4461    ,,,
BEGIN DESCRIPTION:
ALDINE WESTFIELD ROAD U/S FACE
Structure ID: K116-00-00-017
S17-VRR
END DESCRIPTION:
Bridge Culvert--1,0,-1,-1, 0
Deck Dist Width WeirC Skew NumUp NumDn MinLoCord MaxHiCord MaxSubmerge Is_Ogee
5,842,2.6,0, 64, 57, , , .95, 0, 0,1,,
  4528.1  4578.1  4598.1  4619.4  4637.4  4659.4  4679.4  4729.4  4739.4  4803.3
    4805  4851.1  4853.9  4899.3  4902.4  4951.5  4952.9 4959.09  4959.3 4959.41
  4972.5  4977.3  4988.9  5000.9    5011  5018.7  5021.3  5028.9 5029.69  5029.8
 5029.91    5050    5092  5098.8  5142.6  5146.9  5192.4  5219.4  5227.4  5239.4
  5249.4  5269.4  5279.4  5289.4  5299.4  5309.4  5319.4  5339.4  5349.4  5369.4
  5379.7  5389.4  5409.4  5459.4  5489.4  5529.4  5569.4  5570.3  5579.4  5619.4
  5629.4  5639.4  5649.4  5667.4
   90.22    89.4    89.3    88.4   88.46   88.51   88.55   88.96   89.05   89.69
   89.89   89.98      90   90.22   90.23   90.56   90.57   90.59   91.79   91.79
   91.81   91.82   91.83   91.85   91.86   91.87   91.88   91.89   91.89   91.89
   90.69   90.67   90.63   90.62   90.71   90.72   90.26   89.98    89.9   90.04
   90.16   90.39   90.51   90.62   90.74   90.86   90.97   91.21   91.32   91.56
   91.68   91.79   92.02   92.61   92.96   93.51   93.91    93.9   94.09   94.91
   95.12   95.32   95.53   95.63
                                                                                
                                                                                
                                                                                
                                                                                
                                                                                
                                                                                
                                
 4531.68  4578.1  4598.1  4619.4  4637.4  4659.4  4679.4  4729.4  4739.4  4803.3
    4805  4851.1  4853.9  4899.3  4902.4  4951.5  4952.9 4959.09  4959.3 4959.41
  4972.5  4977.3  4988.9  5000.9    5011  5018.7  5021.3  5028.9 5029.69  5029.8
 5029.91    5050    5092  5098.8  5142.6  5146.9  5192.4  5219.4  5227.4  5239.4
  5249.4  5269.4  5279.4  5289.4  5299.4  5309.4  5319.4  5339.4  5349.4  5369.4
  5379.7  5389.4  5409.4  5459.4  5489.4  5529.4  5676.5
   89.91    89.4    89.3    88.4   88.46   88.51   88.55   88.96   89.05   89.69
   89.89   89.98      90   90.22   90.23   90.56   90.57   90.59   91.79   91.79
   91.81   91.82   91.83   91.85   91.86   91.87   91.88   91.89   91.89   91.89
   90.69   90.67   90.63   90.62   90.71   90.72   90.26   89.98    89.9   90.04
   90.16   90.39   90.51   90.62   90.74   90.86   90.97   91.21   91.32   91.56
   91.68   91.79   92.02   92.61   92.96   93.51   93.71
                                                                                
                                                                                
                                                                                
                                                                                
                                                                                
                                                        
BR Coef= 1 , 1 , 0 ,1.25, 0 ,,,.8,0,2,0,
WSPro=,,,, 1 ,,,, 0 ,,,, 0 ,,,,-1 ,-1 ,-1 , 0 , 0 , 0 , 0 , 0
Culvert=2,8,8,860,.013,.5,1,8,2,78.78,4995.5,78.6,4985.92,Culvert #1  , 0 ,3.2
Culvert Bottom n=.013
Culvert=2,8,8,860,.013,.5,1,8,2,78.81,5004.5,78.57,4994.92,Culvert #2  , 0 ,3.2
Culvert Bottom n=.013
BC Design=,, 0 ,, 0 ,,,,,,
BC HTab HWMax=98.02

Type RM Length L Ch R = 1 ,4029    ,60.1,54,35.1
BEGIN DESCRIPTION:
Aldine Westfield Rd. DS - XS 2
Located At: WOOD RIVER RD-D/S FACE 1000' TRIPLE BOX CUL (2 culverts effective)
END DESCRIPTION:
XS GIS Cut Line= 6
       3112248.4      13946409.2      3111570.25      13945959.1
       3111467.3      13945976.2      3111361.96      13945995.2
      3110943.19      13946090.2      3110646.31      13946624.1
#Sta/Elev= 30
  4081.7    97.1  4141.7    96.9  4201.7    94.4  4291.7    93.4  4311.7    92.5
  4731.7    87.7 4860.28   88.47 4888.55   87.39 4966.78   86.45 4982.68   81.32
 4986.05   80.56  4987.7   79.14 4993.55   78.57    4997   78.72 4999.18   78.88
 5001.73   80.27 5008.33    80.5 5009.38   78.54  5010.5   78.39 5011.78   78.57
 5017.85   85.13    5105   85.33    5307    86.8    5337    87.8    5437    88.7
    5447    89.2    5467      91    5527    92.6  6126.5    97.9  6147.3    97.8
#Mann= 3 ,-1 , 0
  4081.7     .08       0 4966.78     .04       0 5017.85     .08       0
#XS Ineff= 2 , 0
       0 4981.92   84.43 4998.92       0   84.43
Permanent Ineff=
       F       F
Bank Sta=4966.78,5017.85
XS Rating Curve= 0
Exp/Cntr=.5,.3

Type RM Length L Ch R = 1 ,3975    ,374.3,389,412
BEGIN DESCRIPTION:
Aldine Westfield Rd. US - XS 1
Cross Section K116-00-00-X1interpolated
END DESCRIPTION:
XS GIS Cut Line= 5
      3111997.92      13946136.7      3111568.19      13945881.4
      3111390.62     13945948.97       3110761.1     13945494.31
      3110604.84      13945404.9
#Sta/Elev= 30
    4369    90.2    4489    88.9    4539    89.2    4609    88.4    4639    87.5
    4659    87.5    4679    85.8    4699    87.6    4739    87.3    4809    85.6
  4938.8    86.1  4958.9    83.6  4988.8   78.36  4988.9    76.2  5018.9    79.1
  5028.9    81.8  5038.9    83.4  5058.8   84.69  5238.9    84.6  5368.9    85.3
  5508.9    86.8  5588.9    85.8  5718.9    87.8  5738.9    87.3  5788.9    88.3
  5875.4    87.4  5895.4    86.5  5915.4    86.8  5955.4    89.3  6015.4    89.8
#Mann= 3 ,-1 , 0
    4369     .08       0  4938.8     .04       0  5058.8     .08       0
Bank Sta=4938.8,5058.8
XS Rating Curve= 0
Exp/Cntr=.3,.1

Type RM Length L Ch R = 1 ,3586.   ,72,72,68.6
BEGIN DESCRIPTION:
DROP STRUCTURE APPROX. 500 FT D/S OF RIVER ROAD - XS 4
Interpolated channel - LIDAR overbanks.
END DESCRIPTION:
XS GIS Cut Line= 3
      3111866.01     13945587.26       3110834.9     13945517.15
      3110646.56     13945413.29
#Sta/Elev= 30
  4515.1   88.58  4525.1   87.87  4565.1   88.82  4655.1   87.55  4685.1      88
  4815.1   84.82  4835.1   85.35  4845.1   84.85  4865.1   82.53  4885.1   82.42
  4935.1   83.58  4955.1    83.3  4965.1   81.55 4994.13   73.91 5008.98   73.91
 5021.81   77.66  5025.1   79.08  5035.1   81.11  5045.1   82.29  5085.1   84.05
  5185.1    84.2  5275.1   85.94  5375.1    84.5  5425.1   86.86  5588.6    88.1
  5658.6   87.66  5678.6   86.57  5698.6   86.42  5738.6   89.71  5763.7   90.04
#Mann= 3 ,-1 , 0
  4515.1      .1       0  4955.1     .04       0  5045.1     .08       0
Bank Sta=4955.1,5045.1
XS Rating Curve= 0
Exp/Cntr=.7,.5

Type RM Length L Ch R = 1 ,3514    ,21,21,21
BEGIN DESCRIPTION:
DROP STRUCTURE APPROX. 500 FT D/S OF RIVER ROAD - XS 3
Upstream Section of Bridge/Culvert/Weir
Replaced this cross section with cross section 3513  and adjusted the flowline to better model the structure. - JJA 3/26/03
END DESCRIPTION:
XS GIS Cut Line= 3
      3111870.57      13945516.8      3110731.82     13945444.35
      3110671.27       13945409.
#Sta/Elev= 30
  4514.9      89  4604.9    87.6  4634.9    88.4  4674.9    86.8  4684.9    86.6
  4724.9    86.9  4784.9    85.4  4841.2   87.12  4859.1   85.29  4887.4   85.71
  4929.9   84.86  4940.9    83.6  4962.6   84.31  4974.5   81.49  4995.1   73.49
  5012.7   73.49  5034.9   81.48  5052.9   84.38  5065.4   82.99    5080   84.12
  5084.9    83.9  5224.9    85.8  5374.9    84.9  5414.9    86.9  5544.9    87.8
  5554.9    87.5  5644.9    87.6    5676    86.3    5686    86.5    5726    89.7
#Mann= 3 ,-1 , 0
  4514.9      .1       0  4962.6     .04       0  5052.9     .08       0
#XS Ineff= 2 , 0
       0  4962.6   84.31  5052.9       0   84.38
Permanent Ineff=
       F       F
Bank Sta=4962.6,5052.9
XS Rating Curve= 0
Exp/Cntr=.7,.5

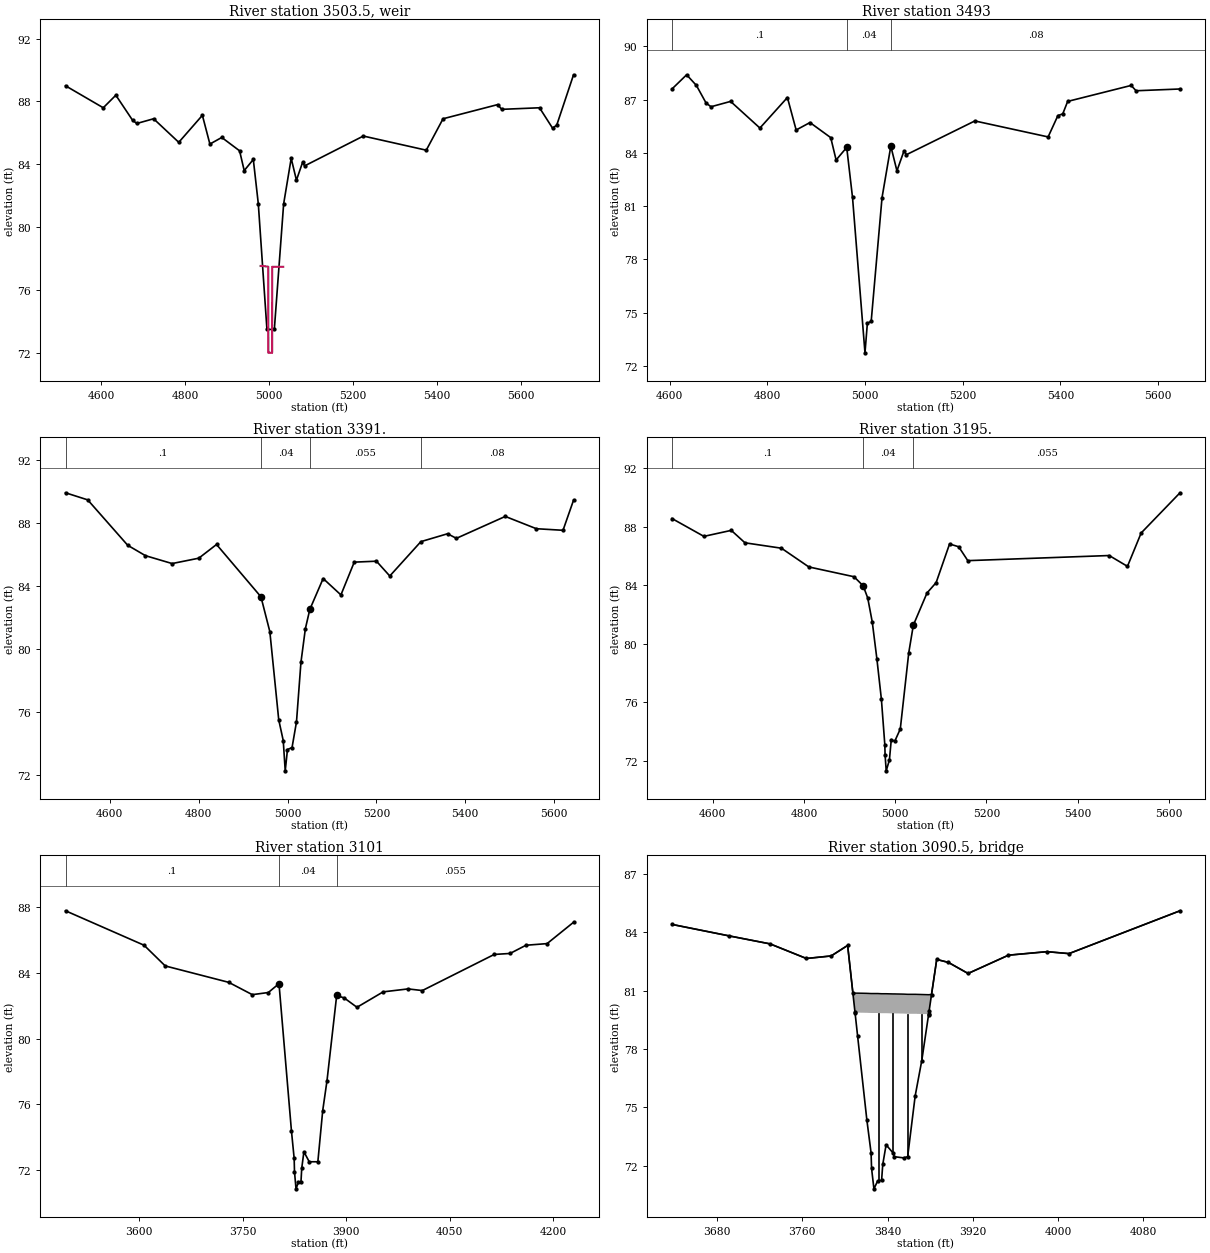
Type RM Length L Ch R = 5 ,3503.5  ,,,
BEGIN DESCRIPTION:
DROP STRUCTURE APPROX. 500 FT D/S OF RIVER ROAD
Structure ID: K116-00-00-304
END DESCRIPTION:
IW Pilot Flow=0
#Inline Weir SE= 17
    4980   77.53 4985.52   77.53 4998.32   77.48 4998.42      72 4998.57      72
 4999.57      72 5000.97      72 5004.17      72 5005.67      72 5006.27      72
 5007.27      72 5007.41      72 5007.52   77.48 5010.97   77.48 5012.75   77.48
 5020.72   77.48 5033.77   77.48
IW Dist,WD,Coef,Skew,MaxSub,Min_El,Is_Ogee,SpillHt,DesHd
10,1,3,0,.95,, 0 ,,,0,0,

Type RM Length L Ch R = 1 ,3493    ,102,102,101.1
BEGIN DESCRIPTION:
DROP STRUCTURE APPROX. 500 FT D/S OF RIVER ROAD - XS 2
Cross Section FIELD_DS
Located At: DROP STRUCTURE APPROX. 500 FT D/S OF RIVER ROAD
END DESCRIPTION:
XS GIS Cut Line= 2
      3111782.53       13945490.      3110744.54      13945425.3
#Sta/Elev= 30
  4604.9    87.6  4634.9    88.4  4654.9    87.8  4674.9    86.8  4684.9    86.6
  4724.9    86.9  4784.9    85.4  4841.2   87.12  4859.1   85.29  4887.4   85.71
  4929.9   84.86  4940.9    83.6  4962.6   84.31  4974.5   81.49    5000   72.74
  5004.9   74.41  5012.7   74.51  5034.9   81.48  5052.9   84.38  5065.4   82.99
    5080   84.12  5084.9    83.9  5224.9    85.8  5374.9    84.9  5394.9    86.1
  5404.9    86.2  5414.9    86.9  5544.9    87.8  5554.9    87.5  5644.9    87.6
#Mann= 3 ,-1 , 0
  4604.9      .1       0  4962.6     .04       0  5052.9     .08       0
Bank Sta=4962.6,5052.9
XS Rating Curve= 0
Exp/Cntr=.7,.5

Type RM Length L Ch R = 1 ,3391.   ,198.7,196,195.9
BEGIN DESCRIPTION:
DROP STRUCTURE APPROX. 500 FT D/S OF RIVER ROAD - XS 1
Interpolated channel - LIDAR overbanks.
END DESCRIPTION:
XS GIS Cut Line= 2
      3111883.79     13945394.89      3110742.26     13945324.94
#Sta/Elev= 30
  4500.2   89.89  4550.2   89.44  4640.2   86.56  4680.2    85.9  4740.2    85.4
  4800.2   85.74  4840.2   86.61  4940.2   83.29  4960.2   81.08  4980.2   75.49
 4990.36   74.17 4994.83   72.25 4999.87    73.6  5010.2   73.73  5020.2   75.36
  5030.2   79.13  5040.2   81.27  5050.2   82.49  5080.2   84.45  5120.2   83.41
  5150.2   85.49  5200.2   85.55  5230.2   84.61  5300.2   86.79  5360.2   87.29
  5380.2      87  5490.2   88.39  5560.2   87.61  5620.2   87.51  5643.9   89.42
#Mann= 4 ,-1 , 0
  4500.2      .1       0  4940.2     .04       0  5050.2    .055       0
  5300.2     .08       0
Bank Sta=4940.2,5050.2
XS Rating Curve= 0
Exp/Cntr=.3,.1

Type RM Length L Ch R = 1 ,3195.   ,59,94,179
BEGIN DESCRIPTION:
Pipeline - XS 4
Interpolated channel - LIDAR overbanks.
END DESCRIPTION:
XS GIS Cut Line= 4
        3111818.     13945361.99      3111469.14     13945168.18
      3111269.72     13945165.41      3110754.58     13945162.64
#Sta/Elev= 30
  4510.8   88.56  4580.8   87.34  4640.8   87.75  4670.8    86.9  4750.8   86.53
  4810.8   85.25  4909.9   84.58  4929.9   83.96  4939.9   83.13  4949.9   81.48
  4959.9   78.99  4969.9    76.2 4977.41   73.09 4977.93   72.42 4980.42   71.31
 4987.45   72.05 4991.56   73.45 4999.11   73.33 5011.29   74.17  5029.9   79.39
  5039.9   81.27  5069.9   83.47  5089.9   84.18  5119.3   86.82  5139.3   86.63
  5159.3   85.68  5469.3   86.03  5509.3   85.29  5539.3   87.57  5624.5   90.32
#Mann= 3 ,-1 , 0
  4510.8      .1       0  4929.9     .04       0  5039.9    .055       0
Bank Sta=4929.9,5039.9
XS Rating Curve= 0
Exp/Cntr=.5,.3

Type RM Length L Ch R = 1 ,3101    ,21,21,21
BEGIN DESCRIPTION:
Pipeline - XS 3
Upstream Section of Bridge/Culvert/Weir
END DESCRIPTION:
XS GIS Cut Line= 4
       3111828.3      13945311.2      3111703.12     13945278.33
      3111256.28     13944989.21      3110806.04      13944961.8
#Sta/Elev= 30
3493.239    87.83607.073    85.73637.715   84.443729.749   83.443763.837   82.69
3787.048   82.823802.522   83.363820.524   74.413824.508   72.713824.968   71.91
3827.189   70.863830.713   71.273834.389    71.33835.462   72.113838.603   73.12
3846.341   72.513858.825   72.513865.874   75.633872.079   77.453886.097   82.64
3896.975   82.493915.513   81.923953.433   82.863989.513   83.044010.196   82.94
4114.349   85.144137.329    85.24160.311    85.74190.953    85.84229.255    87.1
#Mann= 3 ,-1 , 0
3493.239      .1       03802.522     .04       03886.097    .055       0
#XS Ineff= 2 , 0
       03802.522   83.363886.097       0   82.64
Permanent Ineff=
       F       F
Bank Sta=3802.522,3886.097
XS Rating Curve= 0
Skew Angle= 40
Exp/Cntr=.5,.3

Type RM Length L Ch R = 3 ,3090.5  ,,,
BEGIN DESCRIPTION:
PL1_K116-00-00-305
END DESCRIPTION:
Bridge Culvert--1,0,-1,-1, 0
Deck Dist Width WeirC Skew NumUp NumDn MinLoCord MaxHiCord MaxSubmerge Is_Ogee
10,1,2.6,40, 35, 35, , , .95, 0, 0,0,,
3637.7153691.3693729.7483763.8373787.0473802.5223807.4323809.3943809.4623811.869
3820.5243824.5083824.9673827.1893830.7133834.3893835.4613838.6033845.0373846.339
3855.0723858.8253865.8753872.0793878.4293878.5143878.9733881.2263886.0973896.975
3915.5133953.4333989.5134010.1964114.348
    84.4   83.81    83.4   82.65   82.78   83.32   80.89   80.87   80.87   80.87
   80.86   80.85   80.85   80.85   80.85   80.84   80.84   80.84   80.83   80.83
   80.82   80.81   80.81    80.8   80.79   80.79   80.79   80.81    82.6   82.45
   81.88   82.82      83    82.9    85.1
    84.4   83.81    83.4   82.65   82.78   83.32   80.88    79.9   79.87   79.87
   79.86   79.85   79.85   79.85   79.85   79.84   79.84   79.84   79.83   79.83
   79.82   79.81   79.81    79.8   79.79   79.79   79.96    80.8    82.6   82.45
   81.88   82.82      83    82.9    85.1
3637.7153691.3693729.7483763.8373787.0473802.5223807.4323809.3943809.4623811.869
3820.5243824.5083824.9673827.1893830.7133834.3893835.4613838.6033845.0373846.339
3855.0723858.8253865.8753872.0793878.4293878.5143878.9733881.2263886.0973896.975
3915.5133953.4333989.5134010.1964114.348
    84.4   83.81    83.4   82.65   82.78   83.32   80.89   80.87   80.87   80.87
   80.86   80.85   80.85   80.85   80.85   80.84   80.84   80.84   80.83   80.83
   80.82   80.81   80.81    80.8   80.79   80.79   80.79   80.81    82.6   82.45
   81.88   82.82      83    82.9    85.1
    84.4   83.81    83.4   82.65   82.78   83.32   80.88    79.9   79.87   79.87
   79.86   79.85   79.85   79.85   79.85   79.84   79.84   79.84   79.83   79.83
   79.82   79.81   79.81    79.8   79.79   79.79   79.96    80.8    82.6   82.45
   81.88   82.82      83    82.9    85.1
Pier Skew, UpSta & Num, DnSta & Num=  ,3831.6, 2 ,3831.6, 2 , 0 , 0 , 0 ,,
       1       1
   70.23   80.85
       1       1
   70.23   80.85
Pier Skew, UpSta & Num, DnSta & Num=  ,3845.007, 2 ,3845.007, 2 , 0 , 0 , 0 ,,
       1       1
   71.61   80.83
       1       1
   71.61   80.83
Pier Skew, UpSta & Num, DnSta & Num=  ,3858.795, 2 ,3858.795, 2 , 0 , 0 , 0 ,,
       1       1
   71.46   80.81
       1       1
   71.46   80.81
Pier Skew, UpSta & Num, DnSta & Num=  ,3872.048, 2 ,3872.048, 2 , 0 , 0 , 0 ,,
       1       1
    76.3    80.8
       1       1
    76.3    80.8
BR Coef= 1 , 1 , 1 ,1.25, 0 ,,,.8,0,2,0,
WSPro=,,,, 1 ,,,, 0 ,,,, 0 ,,,,-1 ,-1 ,-1 , 0 , 0 , 0 , 0 , 0
BR U #Sta/Elev= 35
3637.715    84.43691.369   83.813729.748    83.43763.837   82.653787.047   82.78
3802.522   83.323807.432   80.883809.394    79.93809.462   79.873811.869   78.67
3820.524   74.373824.508   72.673824.967   71.873827.189   70.823830.713   71.23
3834.389   71.263835.461   72.073838.603   73.083845.037   72.673846.339   72.47
3855.072   72.413858.825   72.473865.875   75.593872.079   77.413878.429   79.76
3878.514   79.793878.973   79.963881.226    80.83886.097    82.63896.975   82.45
3915.513   81.883953.433   82.823989.513      834010.196    82.94114.348    85.1
BR U #Mann= 3
3637.715      .13802.522     .043886.097    .055
BR U Banks=3802.522,3886.097
BR D #Sta/Elev= 35
3637.715    84.43691.369   83.813729.748    83.43763.837   82.653787.047   82.78
3802.522   83.323807.432   80.883809.394    79.93809.462   79.873811.869   78.67
3820.524   74.373824.508   72.673824.967   71.873827.189   70.823830.713   71.23
3834.389   71.263835.461   72.073838.603   73.083845.037   72.673846.339   72.47
3855.072   72.413858.825   72.473865.875   75.593872.079   77.413878.429   79.76
3878.514   79.793878.973   79.963881.226    80.83886.097    82.63896.975   82.45
3915.513   81.883953.433   82.823989.513      834010.196    82.94114.348    85.1
BR D #Mann= 3
3637.715      .13802.522     .043886.097    .055
BR D Banks=3802.522,3886.097
BC Design=,, 0 ,, 0 ,,,,,,
BC HTab HWMax=87.8