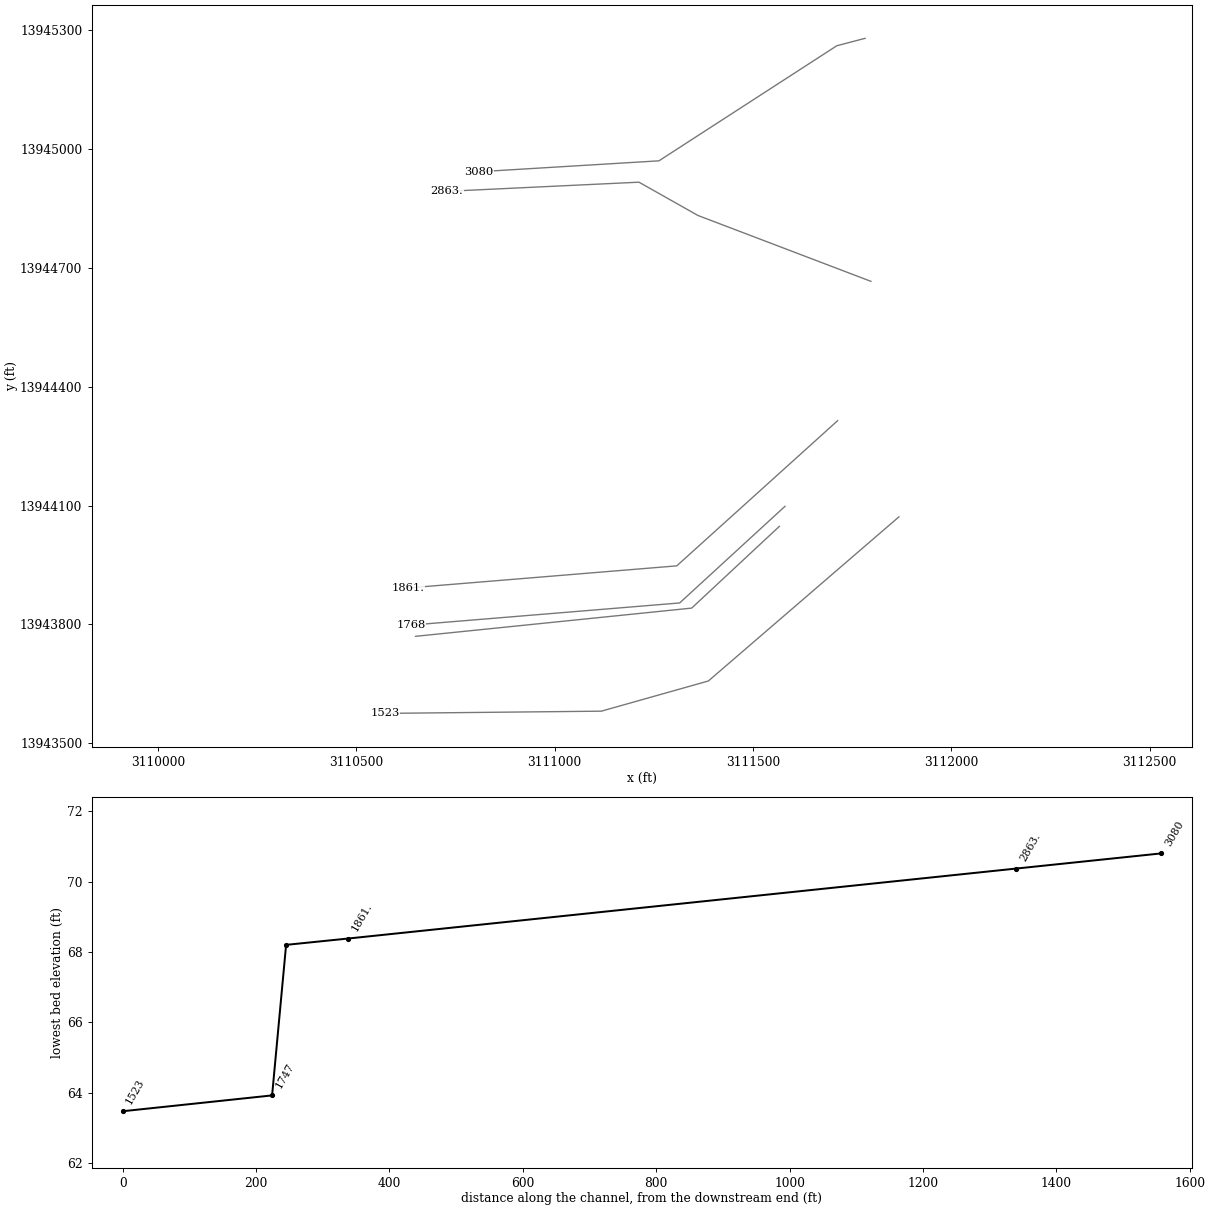
HEC-RAS study K116-00-00.prj: K116-00-00

--- K116-00-00.g01 (geometry) --- (continued)

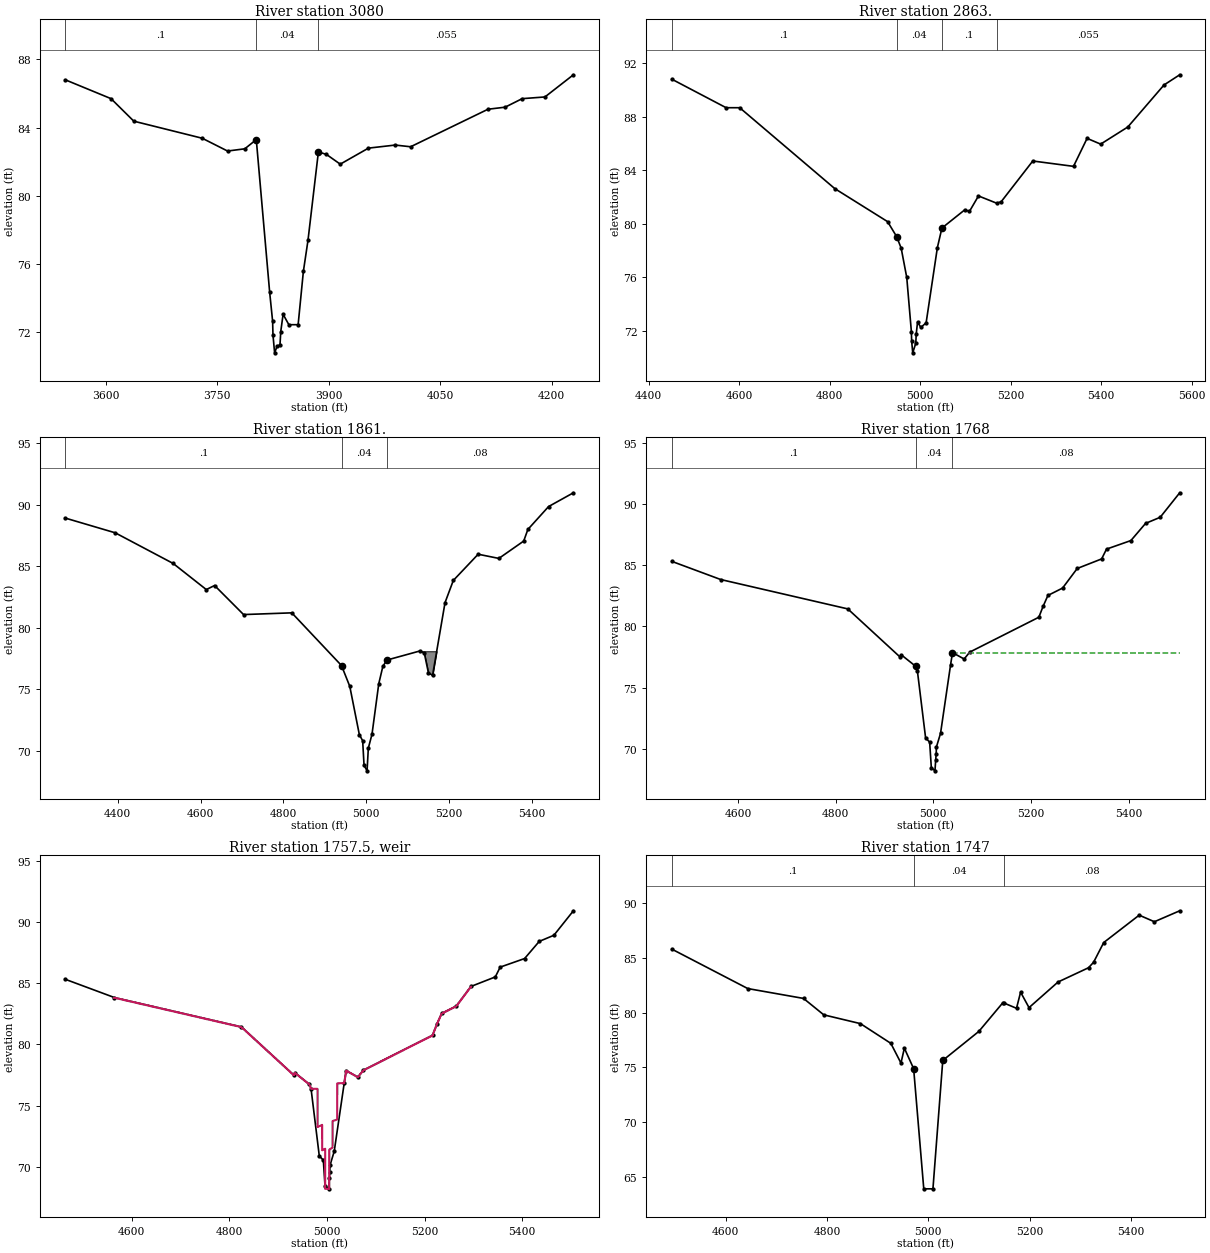
Type RM Length L Ch R = 1 ,3080    ,262,217,119
BEGIN DESCRIPTION:
Pipeline - XS 2
Downstream Section of Bridge/Culvert/Weir
END DESCRIPTION:
XS GIS Cut Line= 4
      3111782.57      13945278.5       3111711.3      13945259.8
      3111262.74      13944969.5      3110807.25      13944941.9
#Sta/Elev= 30
 3545.79    86.83607.073    85.73637.715   84.383729.748   83.383763.837   82.63
3787.047   82.763802.522    83.33820.524   74.353824.508   72.653824.967   71.85
3827.189    70.83830.713   71.213834.389   71.243835.461   72.053838.603   73.06
3846.339   72.453858.825   72.453865.874   75.573872.078   77.393886.097   82.58
3896.975   82.433915.513   81.863953.433    82.83989.513   82.984010.196   82.88
4114.348   85.084137.329    85.24160.311    85.74190.953    85.84229.255    87.1
#Mann= 3 ,-1 , 0
 3545.79      .1       03802.522     .04       03886.097    .055       0
#XS Ineff= 2 , 0
       03802.522    83.33886.097       0   82.58
Permanent Ineff=
       F       F
Bank Sta=3802.522,3886.097
XS Rating Curve= 0
Skew Angle= 40
Exp/Cntr=.5,.3

Type RM Length L Ch R = 1 ,2863.   ,970,1002,1051
BEGIN DESCRIPTION:
Pipeline - XS 1
Interpolated channel - LIDAR overbanks.
END DESCRIPTION:
XS GIS Cut Line= 4
      3111797.33     13944665.49      3111361.12     13944831.67
      3111212.36     13944915.63      3110728.27      13944892.6
#Sta/Elev= 30
  4451.4   90.81  4571.4   88.68  4601.4   88.68  4811.4   82.64  4928.2   80.17
  4948.2   79.05  4958.2   78.19 4970.52      76 4980.78   71.94 4981.29   71.27
 4983.73   70.37 4990.46   71.09 4991.47   71.78 4994.41   72.67 5001.64   72.27
 5013.32   72.61  5038.2   78.23  5048.2   79.69    5099   81.06    5109   80.93
    5129   82.09    5169   81.55    5179   81.65    5249    84.7    5339    84.3
    5369   86.39    5399   85.96    5459   87.24    5539   90.38  5573.7   91.14
#Mann= 4 ,-1 , 0
  4451.4      .1       0  4948.2     .04       0  5048.2      .1       0
    5169    .055       0
Bank Sta=4948.2,5048.2
XS Rating Curve= 0
Exp/Cntr=.3,.1

Type RM Length L Ch R = 1 ,1861.   ,93,93,94
BEGIN DESCRIPTION:
DROP STRUCTURE 1750' USPTREAM K100-00-00 - XS 4
Interpolated channel - LIDAR overbanks.
END DESCRIPTION:
XS GIS Cut Line= 3
      3111713.39     13944314.04      3111307.72     13943947.79
      3110630.07     13943891.99
#Sta/Elev= 30
  4273.8    88.9  4393.8   87.71  4533.8   85.22  4613.8    83.1  4633.8   83.43
  4703.8   81.07  4820.3   81.21  4940.3   76.93  4960.3   75.24 4983.33   71.33
 4991.41   70.82 4994.72   68.83 5002.03   68.38 5005.06   70.22 5013.94   71.35
  5030.3   75.46  5040.3   76.88  5050.3   77.38  5130.3   78.12  5140.3   77.93
  5150.3   76.32  5160.3   76.15  5190.3   82.04  5210.3   83.84  5270.3   85.97
  5320.3   85.63  5380.3   87.04  5390.3   87.98  5440.3   89.84  5500.3   90.96
#Mann= 3 ,-1 , 0
  4273.8      .1       0  4940.3     .04       0  5050.3     .08       0
#Block Obstruct= 1 ,-1
 5129.48 5197.61   78.09
Bank Sta=4940.3,5050.3
XS Rating Curve= 0
Exp/Cntr=.7,.5

Type RM Length L Ch R = 1 ,1768    ,21,21,21
BEGIN DESCRIPTION:
DROP STRUCTURE 1750' USPTREAM K100-00-00 - XS 3
Upstream Section of Bridge/Culvert/Weir
END DESCRIPTION:
XS GIS Cut Line= 3
      3111580.54      13944097.9      3111314.98      13943854.2
      3110637.32      13943798.3
#Sta/Elev= 30
  4464.3    85.3  4564.3   83.82  4824.8   81.42  4931.9   77.49  4934.7   77.66
    4964   76.73 4967.32   76.38  4984.2   70.89  4992.5   70.54  4995.9   68.47
  5003.4    68.2  5004.8   69.06  5005.9   69.59  5006.3   70.14  5014.8   71.26
 5035.27   76.83  5039.3   77.85  5063.2   77.33  5074.5   77.89  5216.2   80.74
  5224.8   81.62  5234.8   82.52  5264.8   83.12  5294.8   84.72  5344.8    85.5
  5354.8    86.3  5404.8      87  5434.8    88.4  5464.8    88.9  5504.8    90.9
#Mann= 3 ,-1 , 0
  4464.3      .1       0    4964     .04       0  5039.3     .08       0
#XS Ineff= 2 , 0
       0 4963.99   76.73 5039.28       0   77.85
Permanent Ineff=
       F       F
Bank Sta=4964,5039.3
XS Rating Curve= 0
Exp/Cntr=.7,.5

Type RM Length L Ch R = 5 ,1757.5  ,,,
BEGIN DESCRIPTION:
DROP STRUCTURE 1750' USPTREAM K100-00-00
Structure ID: K116-00-00-310
END DESCRIPTION:
IW Pilot Flow=0
#Inline Weir SE= 28
  4564.3    83.8  4824.8    81.4  4931.9   77.48  4934.7   77.65  4940.2   77.48
    4964   76.72 4967.32   76.37  4980.6   76.36  4980.8   73.25    4990   73.42
  4990.1   71.35  4996.3   71.47  4996.3    68.2  5004.8    68.2  5004.8    71.4
  5011.3   71.57  5011.5   73.73  5020.9   73.86  5021.1   76.81 5035.27   76.83
  5039.3   77.84  5063.2   77.31  5074.5   77.87  5216.2   80.72  5224.8    81.6
  5234.8    82.5  5264.8    83.1  5294.8    84.7
IW Dist,WD,Coef,Skew,MaxSub,Min_El,Is_Ogee,SpillHt,DesHd
10,1,3,0,.95,,-1 ,,,0,0,

Type RM Length L Ch R = 1 ,1747    ,211,224,233
BEGIN DESCRIPTION:
DROP STRUCTURE 1750' USPTREAM K100-00-00 - XS 2
Cross Section FIELD_DS
Adjusted cross section channel bottom points to conform to the surveyed point of 63.92 to model the drop from the weir upstream. - JJA 3/26/03
END DESCRIPTION:
XS GIS Cut Line= 3
      3111566.41      13944047.4      3111345.26      13943841.2
      3110648.91       13943770.
#Sta/Elev= 25
    4494    85.8  4643.9    82.2  4753.9    81.3  4793.9    79.8  4866.2      79
  4926.2    77.2  4946.2    75.4  4952.9   76.76  4971.2   74.89  4991.2   63.92
  5009.3   63.92  5028.7   75.64  5099.9   78.29  5147.5   80.92  5149.9   80.87
  5174.2    80.4  5182.3   81.87  5198.9   80.46  5256.2    82.8  5316.3    84.1
  5326.3    84.6  5346.3    86.4  5416.3    88.9  5446.3    88.3  5496.3    89.3
#Mann= 3 ,-1 , 0
    4494      .1       0  4971.2     .04       0  5149.9     .08       0
Bank Sta=4971.2,5028.7
XS Rating Curve= 0
Exp/Cntr=.7,.5

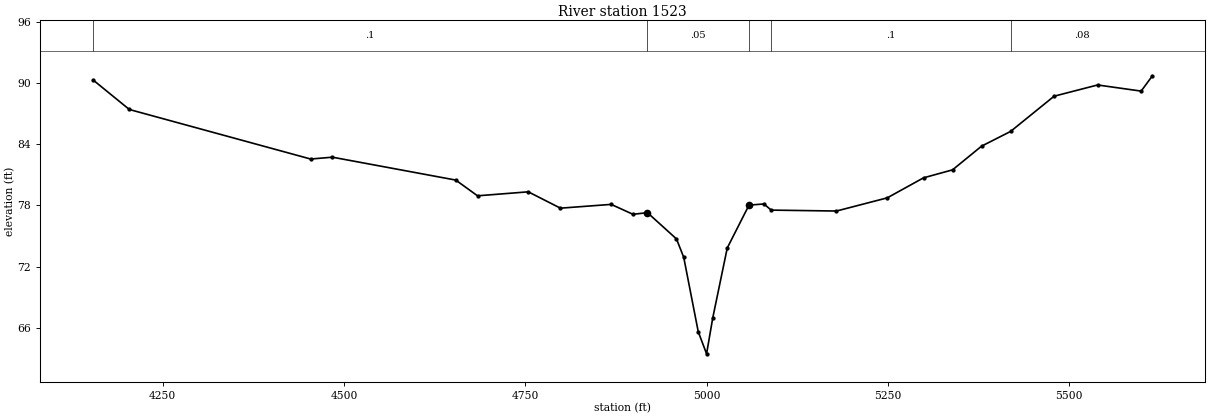
Type RM Length L Ch R = 1 ,1523    ,0,0,0
BEGIN DESCRIPTION:
DROP STRUCTURE 1750' USPTREAM K100-00-00 - XS 1
Extrapolated channel - LIDAR overbanks.
END DESCRIPTION:
XS GIS Cut Line= 4
      3111867.96     13944071.41      3111387.43     13943657.36
       3111117.4     13943581.19      3110571.78     13943575.65
#Sta/Elev= 30
  4154.2   90.28  4204.2   87.39  4454.2   82.54  4484.2   82.72  4654.2   80.48
  4684.2   78.94  4754.2   79.33  4798.5   77.73  4868.5    78.1  4898.5   77.13
  4918.5   77.29  4958.5   74.72  4968.5   72.92  4988.5   65.64    5000   63.47
  5008.5   66.98  5028.5   73.83  5058.5   78.03  5079.1   78.14  5089.1   77.54
  5179.1   77.45  5249.1   78.74  5299.1    80.7  5339.1   81.48  5379.1    83.8
  5419.1   85.24  5479.1   88.69  5539.1   89.79  5599.1   89.19  5614.7   90.69
#Mann= 5 ,-1 , 0
  4154.2      .1       0  4918.5     .05       0  5058.5    .045       0
  5089.1      .1       0  5419.1     .08       0
Bank Sta=4918.5,5058.5
XS Rating Curve= 0
Exp/Cntr=.3,.1

Chan Stop Cuts=-1